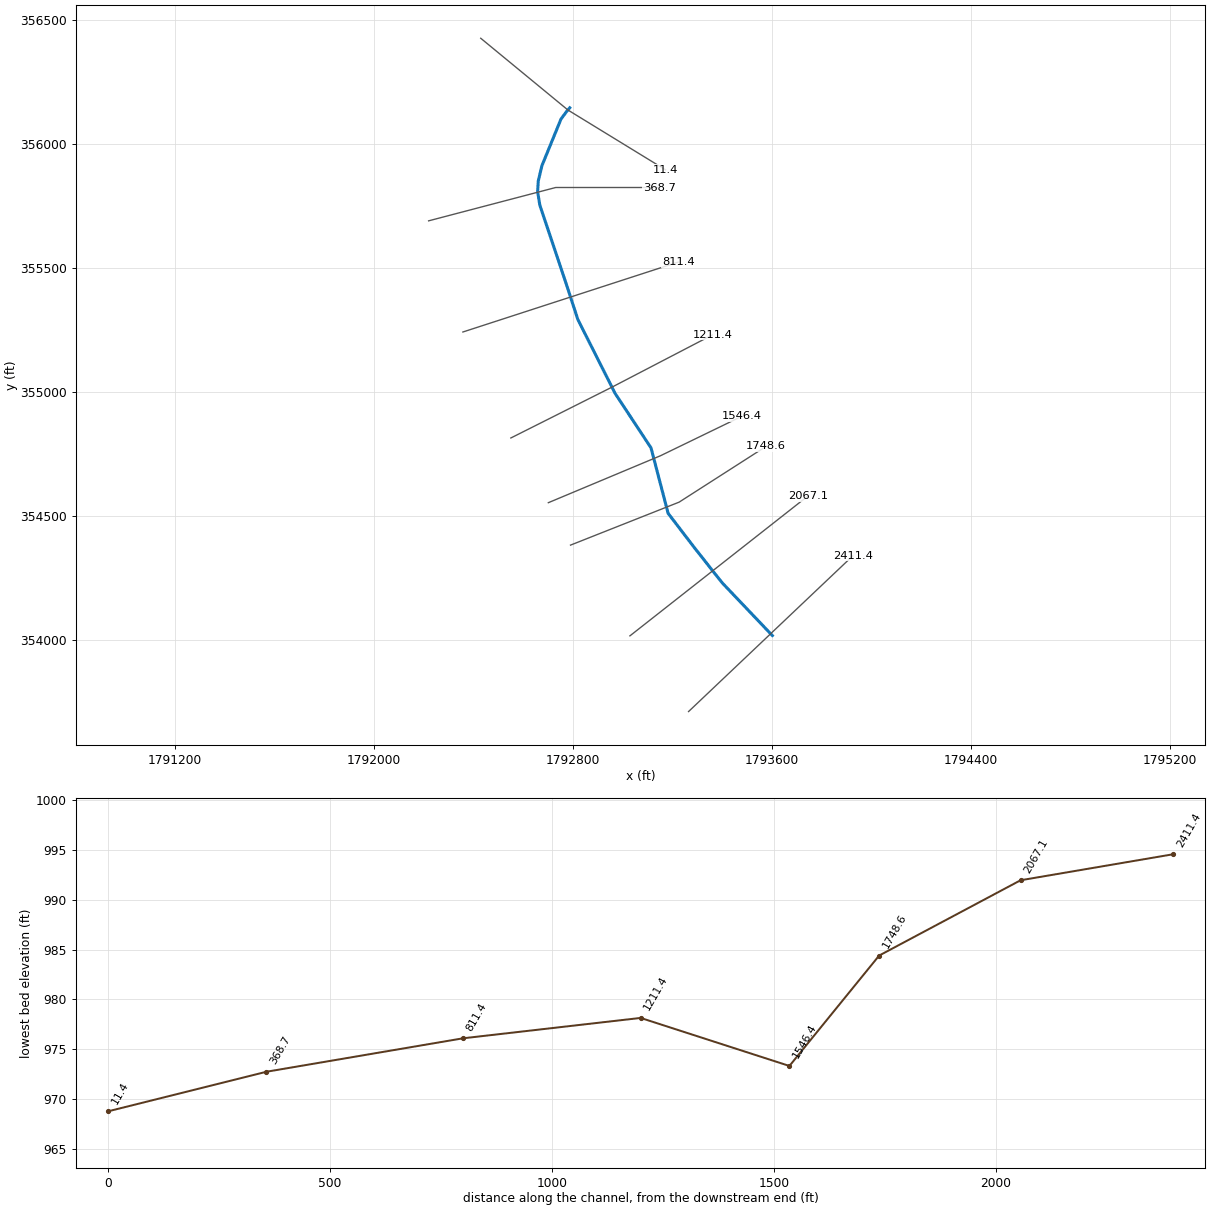
--- HckmnRn.prj (project) ---

Proj Title=HckmnRn
Current Plan=p01
Default Exp/Contr=0,0
English Units
Geom File=g01
Flow File=f01
Plan File=p01
BEGIN DESCRIPTION:
END DESCRIPTION:
DSS Export Rating Curves= 0
DSS Export Rating Curve Sorted= 0
DSS Export Volume Flow Curves= 0
DXF OffsetX= 0
DXF OffsetY= 0
DXF ScaleX= 0
DXF ScaleY= 0

--- HckmnRn.p01 (plan) ---

Plan Title=Floodplain
Program Version=4.00
Geom File=g01
Flow File=f01
K Sum by GR=0
Std Step Tol=0.01
Critical Tol=0.01
Num of Std Step Trials=20
Max Error Tol=0.3
Flow Tol Ratio=0.001
Split Flow NTrial=30
Split Flow Tol=0.02
Split Flow Ratio=0.02
Log Output Level=0
Friction Slope Method=1
Unsteady Friction Slope Method=2
Unsteady Bridges Friction Slope Method=1
Global Log Level=0
CheckData=False
Run HTab=0
Run UNet=0
Run PostProcess=0
UNET Theta=0
UNET Theta Warmup=0
UNET ZTol=0
UNET ZSATol=0
UNET MxIter=0
UNET MaxInSteps=0
UNET DtIC=0
UNET DtMin=0
UNET MaxCRTS=0
UNET WFStab=0
UNET SFStab=0
UNET WFX=0
UNET SFX=0
UNET DSS MLevel=0
UNET DZMax Abort=0
UNET Convert EG Bridges=0
UNET Use Existing IB Tables=0
UNET Froude Limit=0
UNET Froude Power=0
Write IC File=0
Echo Input=False
Echo Output=False
Write Detailed=0

--- HckmnRn.f01 (steady flow) ---

Flow Title=NFF Regression Equation
Program Version=4.00
Number of Profiles=1
Profile Names=P100yr
River Rch & RM=HckmnRn,Main      ,2411.4
788.5428
River Rch & RM=HckmnRn,Main      ,1546.4
812.5216
River Rch & RM=HckmnRn,Main      ,1211.4
903.9883
River Rch & RM=HckmnRn,Main      ,368.7
950.9706
River Rch & RM=HckmnRn,Main      ,11.4
954.5188
Boundary for River Rch & Prof#=HckmnRn,Main      ,1
Up Type=0
Dn Type=3
Dn Slope=0.009944

--- HckmnRn.g01 (geometry) ---

Geom Title=USGS 3m DEM
Program Version=4.00

River Reach=HckmnRn         ,Main
Reach XY= 18
      1793600.91      354019.906     1793400.195      354231.218
     1793367.165      354272.723     1793285.489       354376.48
     1793182.074      354511.834     1793113.242      354775.481
      1793094.65      354803.759     1793079.289      354827.068
     1792969.142      354994.465     1792819.155       355292.32
     1792771.522      355438.768     1792666.464      355752.555
      1792657.61      355806.533     1792660.183      355849.991
     1792674.662      355911.073     1792751.299      356098.853
       1792772.7      356127.892     1792786.455      356144.575

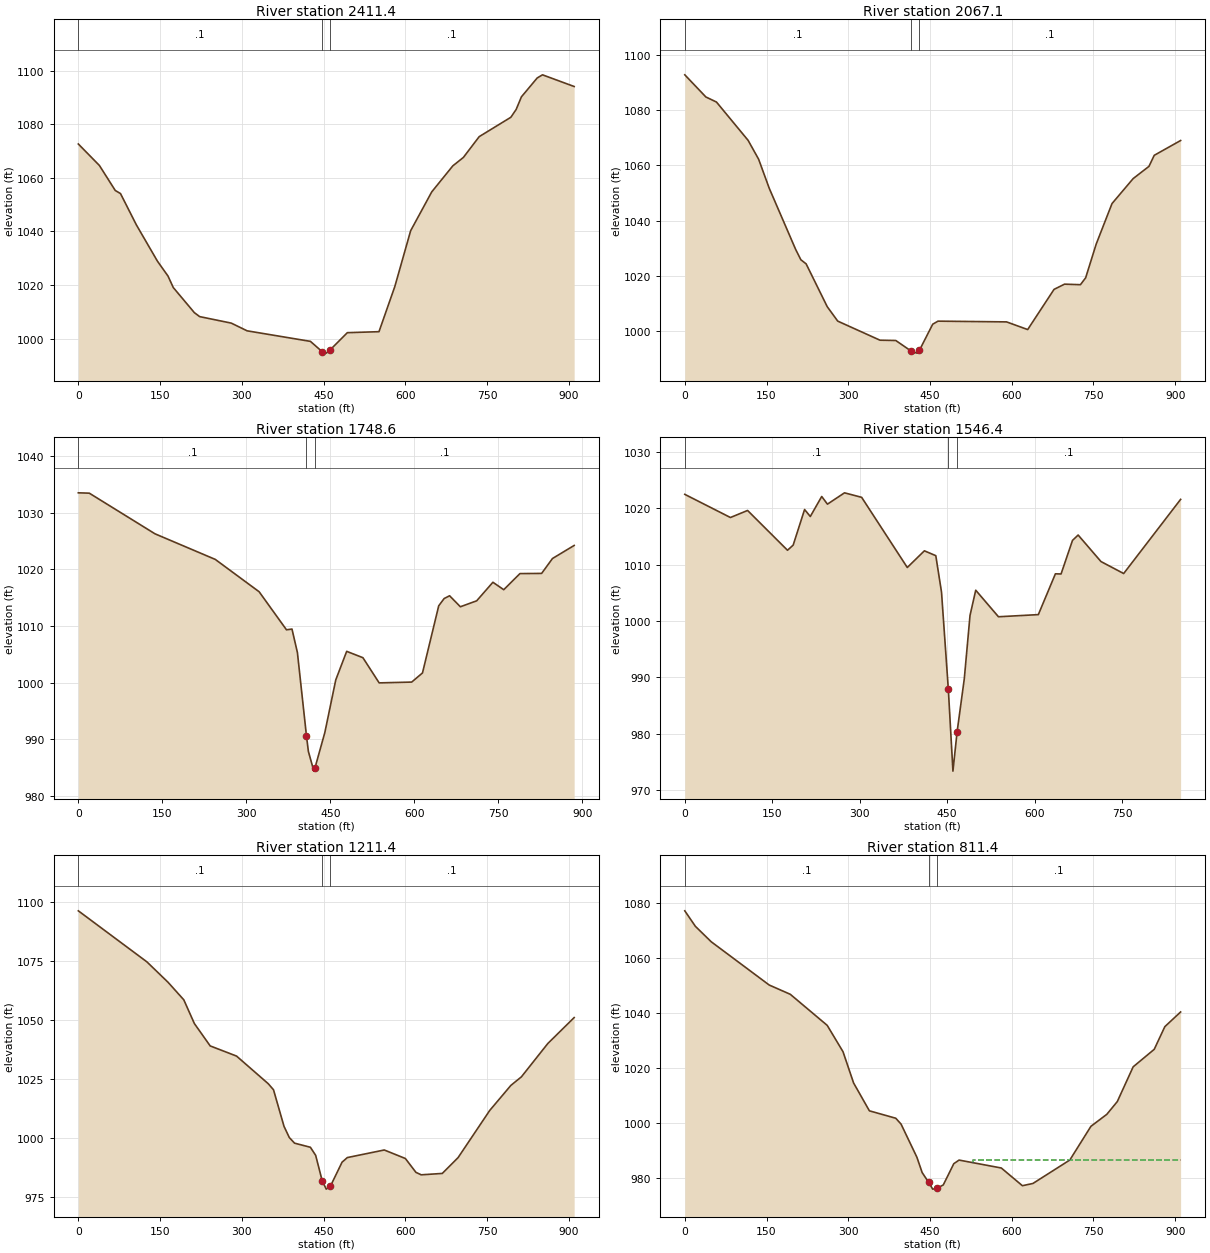
Type RM Length L Ch R = 1 ,2411.4  ,346.371,344.282,342.192
XS GIS Cut Line= 3
     1793264.125      353713.801     1793594.023      354027.157
     1793923.922      354340.513
#Sta/Elev= 30
       0 1072.68    38.7 1064.65    67.8 1055.31    77.4 1054.16   106.5 1042.47
   145.2  1028.9   164.6 1023.34   174.3 1019.04     213 1009.66   222.7 1008.19
   280.7 1005.76   309.8 1002.88     426  998.94   447.5   995.1     455  994.55
   462.5  995.83   493.7 1002.19   551.8 1002.56   580.9 1019.45   609.9 1040.27
   648.6 1054.78   687.3 1064.51   706.7 1067.66   735.7 1075.42   793.8 1082.66
   803.5 1085.56   813.2 1090.29   842.2 1097.35   851.9 1098.52     910 1094.16
#Mann= 3 , 0 , 0
       0      .1       0   447.5    .045       0   462.5      .1       0
Bank Sta=447.5,462.5
XS Rating Curve= 0 ,0
Exp/Cntr=0.3,0.1

Type RM Length L Ch R = 1 ,2067.1  ,325.108,318.49,311.873
XS GIS Cut Line= 3
     1793028.541      354018.628      1793386.06      354300.062
     1793743.579      354581.496
#Sta/Elev= 30
       0 1092.81    38.7 1084.78    58.1 1082.95   116.2 1069.06   135.5 1062.22
   154.9 1051.73   203.3  1029.6     213 1025.78   222.7 1024.29   261.4 1008.78
   280.7 1003.54   358.2  996.63   387.2  996.52   415.7  992.65     426  991.94
   430.7     993     455 1002.42   464.7 1003.53   590.5 1003.26   629.3 1000.48
   677.7 1015.05     697 1016.94   726.1 1016.74   735.7 1019.25   755.1 1031.49
   784.1 1046.15   822.9  1055.2   851.9 1059.63   861.6 1063.64     910    1069
#Mann= 3 , 0 , 0
       0      .1       0   415.7    .045       0   430.7      .1       0
Bank Sta=415.7,430.7
XS Rating Curve= 0 ,0
Exp/Cntr=0.3,0.1

Type RM Length L Ch R = 1 ,1748.6  ,201.74,202.193,202.645
XS GIS Cut Line= 3
     1792789.741      354383.946     1793226.303      354557.021
     1793576.328       354781.76
#Sta/Elev= 30
       0 1033.47    19.6 1033.41     137 1026.24   244.6 1021.73   322.9 1016.03
   371.8 1009.32   381.6 1009.45   391.3 1005.31   407.5  990.59   410.9  987.88
   420.7   984.4   422.5  984.91   440.3  991.21   459.8 1000.48   479.3 1005.52
   508.3  1004.4   537.3  999.96   595.4  1000.1   614.7 1001.71   643.7 1013.55
   653.4 1014.83   663.1 1015.32   682.4 1013.38   711.5 1014.43   740.5  1017.7
   759.8 1016.39   788.8 1019.23   827.5 1019.26   846.9 1021.89   885.6 1024.19
#Mann= 3 , 0 , 0
       0      .1       0   407.5    .045       0   422.5      .1       0
Bank Sta=407.5,422.5
XS Rating Curve= 0 ,0
Exp/Cntr=0.3,0.1

Type RM Length L Ch R = 1 ,1546.4  ,333.435,335.035,336.95
XS GIS Cut Line= 3
     1792700.623      354554.733      1793151.85       354744.02
     1793476.786      354901.846
#Sta/Elev= 30
       0 1022.45    78.3 1018.34   107.7 1019.59   176.2 1012.53   185.9 1013.44
   205.5 1019.76   215.3 1018.52   234.9 1022.07   244.7 1020.71     274 1022.72
   303.4 1021.92   381.7 1009.47     411 1012.43   430.6 1011.57   440.4 1005.11
   452.1  987.87     460  973.34   467.1  980.27   479.5  989.74   489.3 1000.96
   499.1 1005.44   538.1 1000.73   606.5 1001.11   635.8 1008.35   645.5 1008.32
   665.1 1014.28   674.8 1015.23   713.9 1010.53   752.9  1008.4   850.6 1021.56
#Mann= 3 , 0 , 0
       0      .1       0   452.1    .045       0   467.1      .1       0
Bank Sta=452.1,467.1
XS Rating Curve= 0 ,0
Exp/Cntr=0.3,0.1

Type RM Length L Ch R = 1 ,1211.4  ,403.427,400,396.259
XS GIS Cut Line= 3
     1792549.948      354815.286     1792956.324       355019.92
     1793359.859      355230.237
#Sta/Elev= 30
       0 1096.42   125.8 1074.74   164.6 1066.07   193.6 1058.59     213 1048.51
     242 1039.01   290.4 1034.69   348.5 1022.96   358.2 1020.38   377.5 1004.83
   387.2 1000.08   396.9  997.68   425.9  995.94   435.6   992.5   447.5  981.76
     455  978.15   462.5  979.31     484  989.59   493.7  991.56   561.5  994.78
   600.2  991.17   619.6  985.28   629.3  984.23     668  984.82     697  991.55
   755.1  1011.6   793.9 1022.24   813.2 1025.87   861.6 1040.02     910 1051.05
#Mann= 3 , 0 , 0
       0      .1       0   447.5    .045       0   462.5      .1       0
Bank Sta=447.5,462.5
XS Rating Curve= 0 ,0
Exp/Cntr=0.3,0.1

Type RM Length L Ch R = 1 ,811.4   ,444.043,442.749,441.587
XS GIS Cut Line= 3
     1792357.079      355241.939     1792789.767      355382.673
     1793222.455      355523.407
#Sta/Elev= 30
       0 1077.01    19.4  1071.4    48.4 1065.81   154.9 1050.11   193.6 1046.75
   261.4 1035.48   290.4 1025.92   309.8  1014.6   338.8  1004.5   387.2 1001.81
   396.9  999.69     426  987.67   435.6  982.13   447.5  978.58     455  976.11
   462.5   976.4   474.4  977.63   493.7  985.33   503.4  986.64   580.9  983.77
   619.6  977.35   638.9  978.16   706.7  986.67   745.4  998.89   774.5 1003.22
   793.8 1007.86   822.9 1020.45   861.6  1026.8     881 1035.01     910 1040.34
#Mann= 3 , 0 , 0
       0      .1       0   447.5    .045       0   462.5      .1       0
#XS Ineff= 2 , 0
                          528.79          986.68
Permanent Ineff=
       F       F
Bank Sta=447.5,462.5
XS Rating Curve= 0 ,0
Exp/Cntr=0.3,0.1

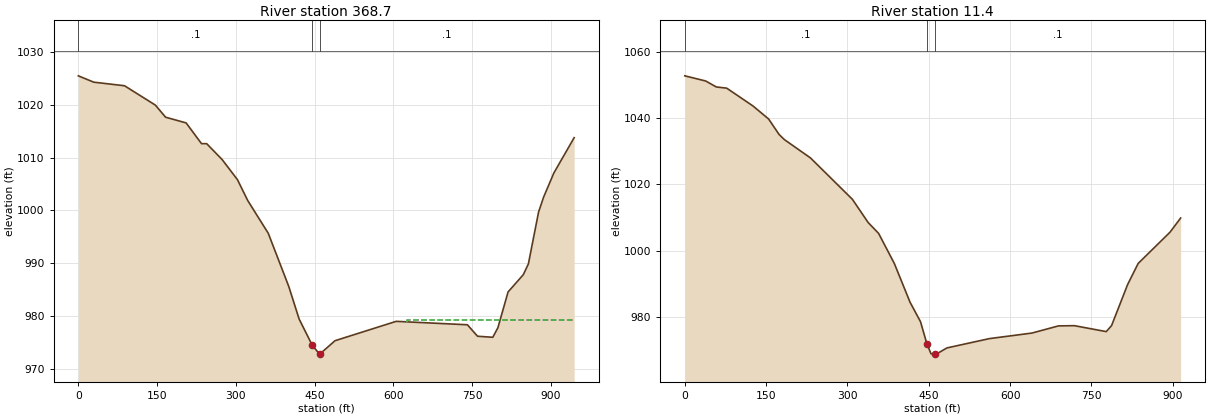
Type RM Length L Ch R = 1 ,368.7   ,378.62,357.251,338.898
XS GIS Cut Line= 3
     1792219.441      355689.473     1792730.237      355823.722
       1793146.8      355823.722
#Sta/Elev= 30
       0 1025.48    29.3 1024.28      88  1023.6   146.7 1019.94   166.3 1017.64
   205.4 1016.56   234.7 1012.63   244.5 1012.63   273.9 1009.63   303.2 1005.81
   322.8 1001.85   361.9  995.65     401  985.57   420.6  979.43   445.9   974.4
   459.7  972.76   460.9  972.84     489   975.3   605.6  978.97   741.3  978.32
   760.6  976.15   789.7  975.95   799.4  977.76   818.8  984.54   847.8  987.81
   857.5  989.85   876.9  999.67   886.6 1002.53     906 1007.07   944.7 1013.76
#Mann= 3 , 0 , 0
       0      .1       0   445.9    .045       0   460.9      .1       0
#XS Ineff= 2 , 0
                          626.22          979.16
Permanent Ineff=
       F       F
Bank Sta=445.9,460.9
XS Rating Curve= 0 ,0
Exp/Cntr=0.3,0.1

Type RM Length L Ch R = 1 ,11.4    ,11.414,11.414,8.266
XS GIS Cut Line= 3
     1792428.859      356424.605     1792779.194      356135.768
     1793171.567      355894.948
#Sta/Elev= 30
       0  1052.7    38.6 1051.14      58 1049.35    77.3 1048.98   125.6 1043.63
   154.6 1039.68   173.9 1035.02   183.6 1033.48   231.9 1027.93   309.1 1015.47
   338.1 1008.48   357.4  1005.2   386.4  996.13   415.4  984.45   434.7  978.57
   446.5  971.89   454.1  968.89   461.5  968.81   463.8  968.79   483.4  970.66
   561.8  973.47   640.2  975.14   689.1   977.3   718.5  977.37   777.3  975.58
   787.1  977.41   816.5  989.71   836.1  996.13   894.8 1005.55   914.4 1009.82
#Mann= 3 , 0 , 0
       0      .1       0   446.5    .045       0   461.5      .1       0
Bank Sta=446.5,461.5
XS Rating Curve= 0 ,0
Exp/Cntr=0.3,0.1

Chan Stop Cuts=-1
Use User Specified Reach Order=0